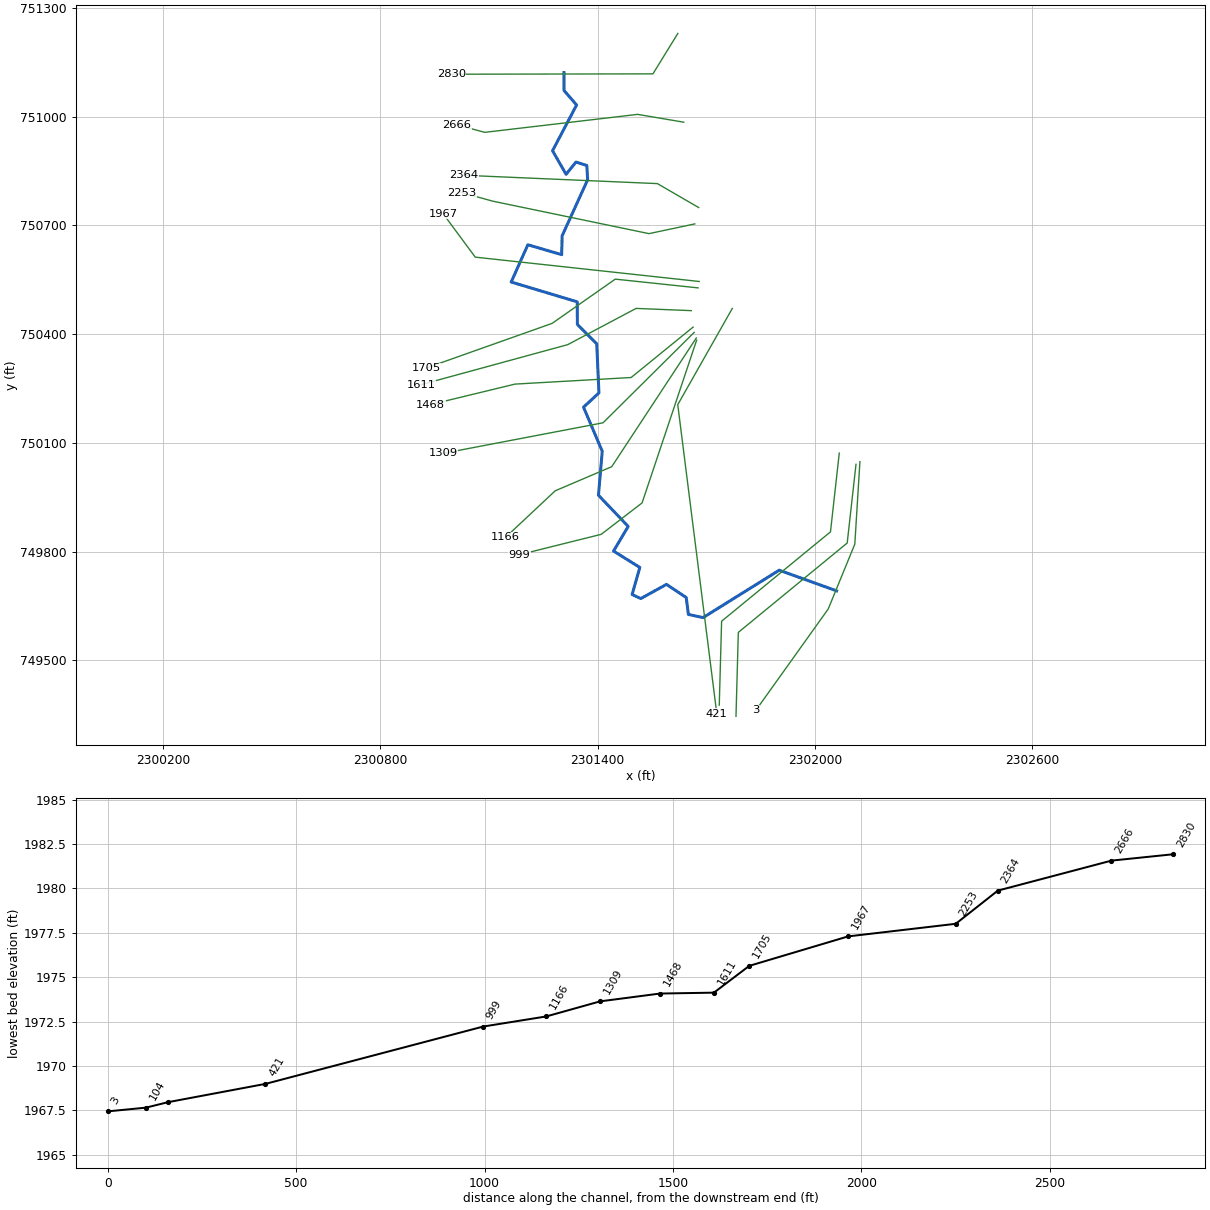
--- CMPFLDRNT1.prj (project) ---

Proj Title=CMPFLDRNT1
Current Plan=p01
Default Exp/Contr=0,0
English Units
Geom File=g01
Flow File=f01
Plan File=p01
BEGIN DESCRIPTION:
----------MODEL BY WOOD PLC 2022----------
AFH study
Randolph County, WV
HEC-RAS Version: RAS 6.2
Vertical Datum: NAVD88
Projection: NAD 1983 StatePlane West Virginia S FIPS 4702 (US Feet)
Terrain: 1-meter LIDAR (FEMA Region III 3DEP collected 2016-2018)
Land Use: 2019 NLCD
Hydrologic Method:
WV SIR2010-5033 regression equations
Additional Model Notes:
Coincident peak modeling; 4 shared structure XSs due to first XS DS of confluence going to critical depth
END DESCRIPTION:
DSS Export Rating Curves= 0
DSS Export Rating Curve Sorted= 0
DSS Export Volume Flow Curves= 0
DXF OffsetX= 0
DXF OffsetY= 0
DXF ScaleX= 0
DXF ScaleY= 0

--- CMPFLDRNT1.p01 (plan) ---

Plan Title=Floodplain
Program Version=6.20
Short Identifier=Floodplain
Geom File=g01
Flow File=f01
Subcritical Flow
K Sum by GR= 0
Std Step Tol= 0.01
Critical Tol= 0.01
Num of Std Step Trials= 20
Max Error Tol= 0.3
Flow Tol Ratio= 0.001
Split Flow NTrial= 30
Split Flow Tol= 0.02
Split Flow Ratio= 0.02
Log Output Level= 0
Friction Slope Method= 1
Unsteady Friction Slope Method= 2
Unsteady Bridges Friction Slope Method= 1
Parabolic Critical Depth
Global Vel Dist= 0 , 0 , 0
Global Log Level= 0
CheckData=True
Encroach Param=-1 ,0,0, 0
Mapping Interval=1HOUR
Computation Time Step Use Courant=        0
Computation Time Step Use Time Series=    0
Computation Time Step Count To Double=0
Computation Time Step Max Doubling=0
Computation Time Step Max Halving=0
Computation Time Step Residence Courant=0
Run HTab= 0
Run UNet= 0
Run Sediment= 0
Run PostProcess= 0
Run WQNet= 0
Run RASMapper=-1
UNET Theta= 0
UNET Theta Warmup= 0
UNET ZTol= 0
UNET ZSATol= 0
UNET MxIter= 0
UNET Max Iter WO Improvement= 0
UNET MaxInSteps= 0
UNET DtIC= 0
UNET DtMin= 0
UNET MaxCRTS= 0
UNET WFStab= 0
UNET SFStab= 0
UNET WFX= 1
UNET SFX= 1
UNET Gravity=32.174
UNET 1D Methodology=Finite Difference
UNET DSS MLevel= 1
UNET Pardiso=0
UNET DZMax Abort= 0
UNET Use Existing IB Tables= 0
UNET Froude Reduction=False
UNET Froude Limit= 0
UNET Froude Power= 0
UNET D1 Cores= 0
UNET WindReference=Eulerian
UNET WindDragFormulation=Hsu (1988)
UNET D2 Coriolis=0
UNET D2 Cores= 0
UNET D2 Theta= 1
UNET D2 Theta Warmup= 1
UNET D2 Z Tol= 0.01
UNET D2 Volume Tol= 0.01
UNET D2 Max Iterations= 20
UNET D2 Equation= 0
UNET D2 RampUpFraction=0.1
UNET D2 TimeSlices= 1
UNET D2 Turbulence Formulation=Non-Conservative (original)
UNET D2 Eddy Viscosity=0.3
UNET D2 Transverse Eddy Viscosity=0.1
UNET D2 Smagorinsky Mixing=0
UNET D2 BCVolumeCheck=0
UNET D2 Cores=0
UNET D2 SolverType=PARDISO (Direct)
UNET D2 Minimum Iterations= 2147483647
UNET D2 Maximum Iterations= 2147483647
UNET D2 Restart Number= 10
UNET D2 Relaxation Coeff=1.3
UNET D2 SOR Precondition Iterations= 10
UNET D2 ILUT Maximum Fill= 8
UNET D2 ILUT Tolerance=1E-08
UNET D1D2 MaxIter= 0
UNET D1D2 ZTol=0.01
UNET D1D2 QTol=0.1
UNET D1D2 MinQTol=1
Write IC File= 0
Write IC File at Fixed DateTime=0
Write IC File at Sim End=0
Echo Input=False
Echo Parameters=False
Echo Output=False
Write Detailed= 0
HDF Write Warmup=0
HDF Write Time Slices=0
HDF Flush=0
HDF Compression= 1
HDF Chunk Size= 1
HDF Spatial Parts= 1
HDF Use Max Rows=0
HDF Fixed Rows= 1
Calibration Method= 0
Calibration Iterations= 20
Calibration Max Change=0.05
Calibration Tolerance=0.2
Calibration Maximum=1.5
Calibration Minimum=0.5
Calibration Optimization Method= 1
WQ AD Non Conservative
WQ ULTIMATE=-1
WQ Max Comp Step=1HOUR
WQ Output Interval=15MIN
WQ Output Selected Increments= 0
WQ Output face flow=0
WQ Output face velocity=0
WQ Output face area=0
WQ Output face dispersion=0
WQ Output cell volume=0
WQ Output cell surface area=0
WQ Output cell continuity=0
WQ Output cumulative cell continuity=0
WQ Output face conc=0
WQ Output face dconc_dx=0
WQ Output face courant=0
WQ Output face peclet=0
WQ Output face adv mass=0
WQ Output face disp mass=0
WQ Output cell mass=0
WQ Output cell source sink temp=0
WQ Output nsm pathways=0
WQ Output nsm derived pathways=0
WQ Create Restart=0
WQ Fixed Restart=0
WQ System Summary=0
WQ Write To DSS=0
Sorting and Armoring Iterations= 10
XS Update Threshold= 0.02
Bed Roughness Predictor= 0
Hydraulics Update Threshold= 0.02
Energy Slope Method= 1
Volume Change Method= 1
Sediment Retention Method= 0
Sediment TS Multiplier= 1
Warm Up Method= 0
XS Weighting Method= 0
Number of US Weighted Cross Sections= 1
Number of DS Weighted Cross Sections= 1
Upstream XS Weight=0
Main XS Weight=1
Downstream XS Weight=0
Number of DS XS's Weighted with US Boundary= 1
Upstream Boundary Weight= 1
Weight of XSs Associated with US Boundary= 0
Number of US XS's Weighted with DS Boundary= 1
Downstream Boundary Weight= 0.5
Weight of XSs Associated with DS Boundary= 0.5
Percentile Method= 0
Sediment Output Level= 3
Mass or Volume Output= 0
Output Increment Type= 1
Profile and TS Output Increment= 1
Transport Output Increment 1
XS Output Flag= 0
XS Output Increment= 10
Read HDF5 Sediment Hotstart= 0
Sediment Hotstart Type= 0
Write Gradation File= 0
Read Gradation Hotstart= 0
Write HDF5 File= 1
Write Binary Output= 1
Write DSS Sediment File= 0
DSS Sediment Output Type= 1
SV Curve= 0
Specific Gage Flag= 0
Subcell Erosion Methods= 0
Subcell Deposition Methods= 0
Advection Scheme= 1
Matrix Solver= 0
Implicit Weighting Factor= 1
Maximum Outer Loop Convergence Iterations= 5
Convergence Maximum Absolute= 0.001
Convergence RMSE= 0.0001
Grain Fractions Max Abs Error= 0.001
Max Subgrid Regions= 1
Max Subgrid Length Scale= 3.402823E+38
Initial Layer Thickness= 3.402823E+38
Min Layer Thickness= 3.402823E+38
Max Layer Thickness= 3.402823E+38
Number of Layers= 5

--- CMPFLDRNT1.f01 (steady flow) ---

Flow Title=Flow
Program Version=6.20
Number of Profiles= 1
Profile Names=P100yr
River Rch & RM=CMPFLDRNT1,Main            ,2830
     331
River Rch & RM=CMPFLDRNT1,Main            ,421
     623
Boundary for River Rch & Prof#=CMPFLDRNT1,Main            , 1
Up Type= 0
Dn Type= 1
Dn Known WS=1972.1
DSS Import GetInterval= 0
DSS Import GetPeak= 0
DSS Import FillOption= 0

--- CMPFLDRNT1.g01 (geometry) ---

Geom Title=Geometry
Program Version=6.20

River Reach=CMPFLDRNT1      ,Main
Reach XY= 30
2301306.86300004751122.1400000162301307.01400004751072.552000001
     2301341.737751032.6210000072301275.33000001750906.319000021
2301312.65700002750841.2150000042301340.00100003750875.070000023
2301369.94900002750865.5209999982301372.11900003750826.024000019
2301301.80600001750671.5110000072301300.50400001750619.427000016
2301207.18800002750646.7709999982301161.18100002750543.906000018
2301343.47300003750489.2189999972301343.90700001750426.718999997
     2301397.292750373.3330000042301403.36900002750237.917000011
2301360.83400004750198.420000017     2301412.483750076.892000005
2301402.06700002749955.364999995     2301484.098749869.427000001
2301443.73300003749801.2850000112301516.21600002749756.145999998
2301494.94900003749681.4930000012301518.82000001749670.208000004
2301589.73700003749709.359999999     2301644.277749673.062000006
2301650.29800002749626.4590000212301690.81000003749617.663000003
     2301900.992749748.5620000062302059.34300002 749691.46800001

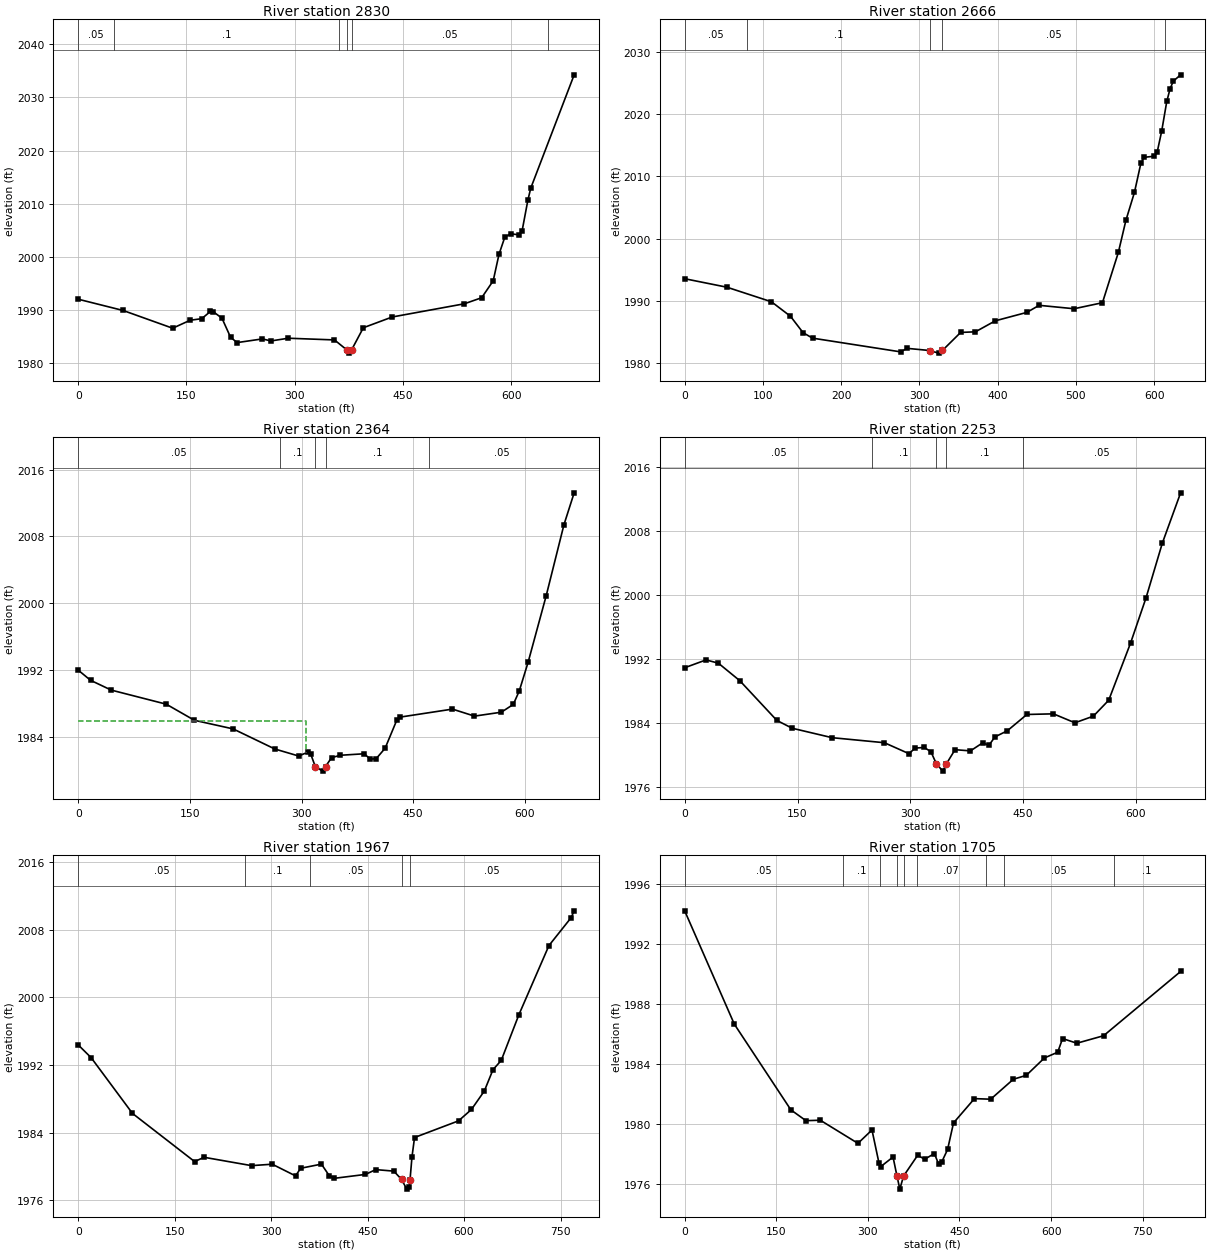
Type RM Length L Ch R = 1 ,2830    ,161.9,164.4,161.6
XS GIS Cut Line= 3
2301621.08689904751229.9606316962301552.40323302751118.474101349
2300995.95644074751117.478685899
#Sta/Elev= 30
       0 1992.06    62.3 1989.94   130.9 1986.61   155.2 1988.11   171.2  1988.4
   183.2 1989.76   187.2 1989.71   199.2  1988.5   211.2  1984.9   220.3 1983.91
   255.2  1984.6   267.2 1984.22   291.2 1984.73   355.2 1984.41     372 1982.57
   375.2 1981.93   379.2 1982.61   395.2  1986.7   435.2 1988.72   535.2  1991.2
   559.2 1992.34   575.2 1995.52   583.2 2000.48   591.2 2003.69   599.2 2004.35
   611.2 2004.16   615.2 2004.86   623.2 2010.63   627.2 2012.91   687.4 2034.22
#Mann= 6, -1 ,  0
       0    0.05       0      50     0.1       0  360.95    0.05       0
     372   0.045       0   379.2    0.05       0  650.95     0.1       0
Bank Sta=372,379.2
XS Rating Curve= 0 ,0
Exp/Cntr(USF)=0,0
Exp/Cntr=0.3,0.1

Type RM Length L Ch R = 1 ,2666    ,296,301.5,295.5
XS GIS Cut Line= 4
 2301637.4865298 750985.034064482301510.23779489751006.653990337
2301088.10987483750957.0553251912301011.13967381750977.864385622
#Sta/Elev= 30
       0 1993.54    54.1 1992.17   110.9 1989.83   135.2  1987.5   151.3 1984.86
   163.4 1983.98   276.1 1981.77   284.2 1982.34   313.1 1981.99   324.5 1981.57
  329.391981.999   352.7  1984.9   371.6    1985     397 1986.77   437.2 1988.12
     453 1989.26   497.7 1988.71   533.9 1989.68   554.2 1997.76   563.9 2002.94
   574.8 2007.43     583 2012.11   587.2 2013.07   599.6 2013.24   603.8 2013.88
   609.6 2017.28   616.1 2022.05   620.3 2024.09   624.5 2025.33   633.8 2026.34
#Mann= 5, -1 ,  0
       0    0.05       0      80     0.1       0   313.1   0.045       0
  329.39    0.05       0   614.1    0.06       0
Bank Sta=313.1,329.39
XS Rating Curve= 0 ,0
Exp/Cntr(USF)=0,0
Exp/Cntr=0.3,0.1

Type RM Length L Ch R = 1 ,2364    ,112.6,111.7,110.1
XS GIS Cut Line= 3
2301678.50346181750749.5829390852301564.75998393750815.543655011
2301030.47834862750838.597567495
#Sta/Elev= 30
       0 1991.98    16.6 1990.76    44.3 1989.59   118.3  1987.9   156.1 1985.97
   208.1 1984.94   264.2 1982.53   296.2 1981.69   308.2 1982.14   312.2 1981.96
   318.51980.431   328.3 1979.88  332.25 1980.42   340.3 1981.49   352.2 1981.78
   384.3 1981.96   392.3 1981.32   400.3 1981.37   412.3 1982.62   428.3 1986.05
   432.4 1986.35   502.8 1987.31   532.4 1986.47   568.5 1986.94   584.5 1987.87
   592.5 1989.47   604.5 1992.94   628.7 2000.88   652.6  2009.4   666.3 2013.22
#Mann= 5, -1 ,  0
       0    0.05       0  271.49     0.1       0   318.5   0.045       0
  332.25     0.1       0  471.49    0.05       0
#XS Ineff= 2 , 0
          305.78 1985.83
Permanent Ineff=
       F       F
Bank Sta=318.5,332.25
XS Rating Curve= 0 ,0
Exp/Cntr(USF)=0,0
Exp/Cntr=0.3,0.1

Type RM Length L Ch R = 1 ,2253    ,278.7,285.5,279.5
XS GIS Cut Line= 4
2301667.96520423750704.3347620992301541.54744214750677.458544961
2301110.53255248 750767.045935422301023.93140837 750790.93590621
#Sta/Elev= 30
       0 1990.93    28.4 1991.91    44.8  1991.5    73.3 1989.31   122.5 1984.35
   142.9 1983.37     196 1982.19   265.5 1981.56   298.2 1980.19   306.3 1980.89
   318.6 1980.97   327.4 1980.42  334.481978.951   343.1 1978.01     348 1978.93
   359.4 1980.69   379.9 1980.54   396.2 1981.55   404.4 1981.23   412.5 1982.29
   428.9 1983.05   454.9 1985.09   490.2 1985.17   518.8 1984.05   543.3 1984.88
   563.7 1986.87   592.7    1994   613.4 1999.69   634.9 2006.48   659.3 2012.79
#Mann= 5, -1 ,  0
       0    0.05       0  249.24     0.1       0  334.48   0.045       0
     348     0.1       0  449.24    0.05       0
Bank Sta=334.48,348
XS Rating Curve= 0 ,0
Exp/Cntr(USF)=0,0
Exp/Cntr=0.3,0.1

Type RM Length L Ch R = 1 ,1967    ,253.4,262.3,263.8
XS GIS Cut Line= 3
2301680.11991274750545.4256706632301061.96691858750612.616213507
2300973.07631893750732.762858265
#Sta/Elev= 30
       0 1994.37    20.1 1992.86    84.4 1986.26     181 1980.56   195.7 1981.07
   269.5 1980.08   301.7 1980.25   337.9 1978.87     346 1979.77   378.2 1980.26
   390.2 1978.91   398.3 1978.58   446.6 1979.04   462.7 1979.61   490.8 1979.43
   502.9 1978.44   510.9  1977.3     515 1977.56     516 1978.42     519  1981.1
     523 1983.41   591.4 1985.38   611.5 1986.73   631.5 1988.91     645 1991.44
   657.8 1992.53   685.3 1997.95     732 2006.13   766.5 2009.43   771.2 2010.24
#Mann= 5, -1 ,  0
       0    0.05       0     260     0.1       0     360    0.05       0
   502.9   0.045       0     516    0.05       0
Bank Sta=502.9,516
XS Rating Curve= 0 ,0
Exp/Cntr(USF)=0,0
Exp/Cntr=0.3,0.1

Type RM Length L Ch R = 1 ,1705    ,92.3,93.8,91.5
XS GIS Cut Line= 4
2301677.07315605750527.729314357 2301448.4909293750551.893721186
2301274.11534488750429.7655028892300926.01726814 750306.33110044
#Sta/Elev= 30
       0 1994.18    81.3 1986.63   173.9 1980.92   198.6  1980.2   222.1 1980.23
   283.7 1978.69   306.7 1979.58   318.1 1977.39   321.1 1977.14   341.2 1977.78
  347.671976.503   352.3 1975.64   358.4 1976.51   381.6  1977.9   392.9 1977.63
   408.9 1978.01   415.8 1977.31   420.7 1977.43   430.5 1978.28   440.2 1980.05
   474.5 1981.67   501.1 1981.63   538.2 1982.96   559.4 1983.22   589.1 1984.38
   610.8 1984.76   618.8 1985.67   642.2 1985.36     686 1985.86   812.1 1990.14
#Mann= 9, -1 ,  0
       0    0.05       0  259.86     0.1       0  319.86    0.05       0
  347.67   0.045       0   358.4    0.05       0  379.86    0.07       0
  492.75     0.1       0  522.75    0.05       0  702.75     0.1       0
Bank Sta=347.67,358.4
XS Rating Curve= 0 ,0
Exp/Cntr(USF)=0,0
Exp/Cntr=0.3,0.1

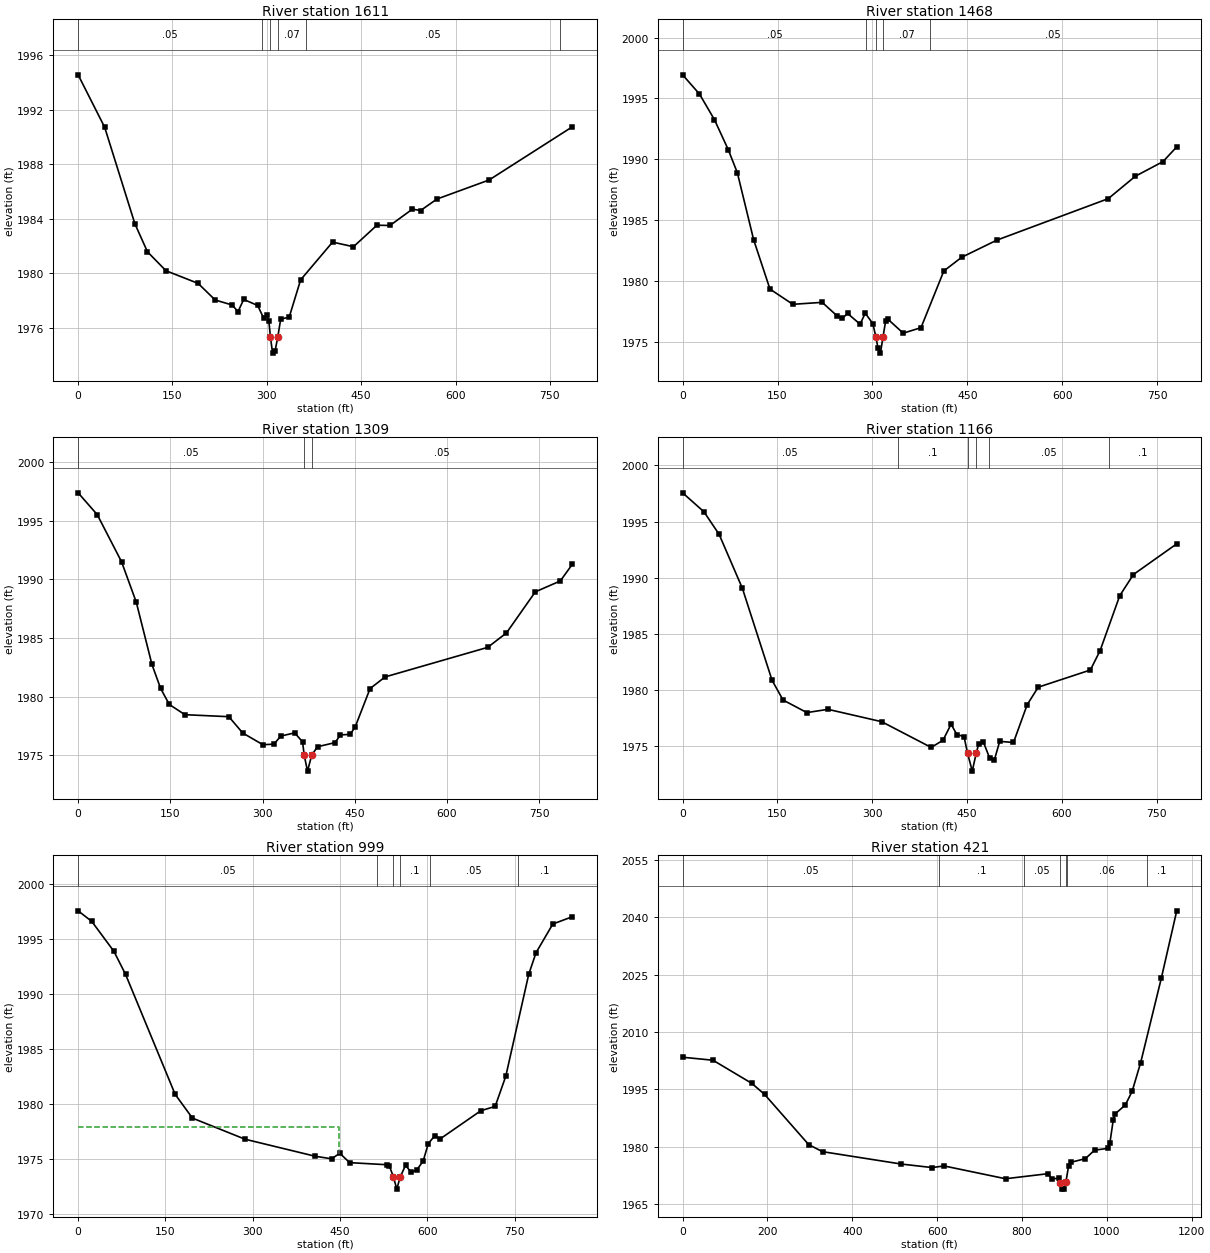
Type RM Length L Ch R = 1 ,1611    ,143.9,142.9,139.2
XS GIS Cut Line= 4
 2301658.3243123750464.9387987722301505.93972496750471.083338584
2301317.29227532750371.0788533932300912.65026979750260.666986358
#Sta/Elev= 30
       0 1994.56    42.2 1990.71    90.2 1983.63   110.2 1981.57   139.6 1980.18
   190.7 1979.25   217.9 1978.03   245.1 1977.66   254.1 1977.17   263.2 1978.07
   285.4 1977.63   294.9  1976.7   300.2 1976.91   303.2 1976.49  305.63 1975.35
   309.1 1974.13     313 1974.26   317.5 1975.35     322 1976.62   335.6 1976.78
   353.7 1979.51   404.5 1982.28   437.7 1981.94     475 1983.52   495.7  1983.5
   531.4  1984.7   544.4  1984.6   570.4 1985.44   653.3 1986.84   785.5 1990.74
#Mann= 6, -1 ,  0
       0    0.05       0  292.51    0.07       0  305.63   0.045       0
   317.5    0.07       0  362.51    0.05       0  766.02     0.1       0
Bank Sta=305.63,317.5
XS Rating Curve= 0 ,0
Exp/Cntr(USF)=0,0
Exp/Cntr=0.3,0.1

Type RM Length L Ch R = 1 ,1468    ,154.1,158.9,156.6
XS GIS Cut Line= 4
2301663.28144185  750419.57253772301492.27012677750280.374777778
2301171.67675919750262.1689849782300939.00351832750205.775764038
#Sta/Elev= 30
       0 1996.94    26.7 1995.36    50.4 1993.25    72.1  1990.8    86.5  1988.9
   112.3 1983.39   138.1 1979.34   174.2 1978.09   220.6 1978.25   244.6 1977.12
   252.6 1976.94   260.7 1977.34   280.5 1976.46   288.7 1977.36   300.7  1976.5
   305.5  1975.4   308.7 1974.53   312.7 1974.08   316.8 1975.43   320.8 1976.68
   324.8 1976.85   348.7 1975.72   376.8 1976.17   412.9 1980.83     441 1981.95
   496.6 1983.36   672.8 1986.77   715.6 1988.61   759.2 1989.81     781 1991.02
#Mann= 5, -1 ,  0
       0    0.05       0   290.5    0.07       0   305.5   0.045       0
   316.8    0.07       0   390.5    0.05       0
Bank Sta=305.5,316.8
XS Rating Curve= 0 ,0
Exp/Cntr(USF)=0,0
Exp/Cntr=0.3,0.1

Type RM Length L Ch R = 1 ,1309    ,139.5,143,142.6
XS GIS Cut Line= 3
2301666.26558214 750404.935416542301414.70312954750155.356115764
 2300973.1837192750071.011698566
#Sta/Elev= 30
       0 1997.36    31.1  1995.5    70.6 1991.49    94.6 1988.04   120.1 1982.73
   134.2 1980.69   148.4 1979.32   173.8 1978.45   245.2 1978.28   267.8 1976.89
   300.7 1975.89   318.5 1975.94   329.8 1976.63   352.3  1976.9   365.1 1976.14
  367.87 1974.98   373.2 1973.64     380    1975   389.5 1975.72     418 1976.07
   426.8 1976.73   442.5 1976.77   450.7  1977.4     475 1980.68   499.5 1981.67
   666.4 1984.19   696.9 1985.42   743.8 1988.92   784.5 1989.85   803.9 1991.26
#Mann= 3, -1 ,  0
       0    0.05       0  367.87   0.045       0     380    0.05       0
Bank Sta=367.87,380
XS Rating Curve= 0 ,0
Exp/Cntr(USF)=0,0
Exp/Cntr=0.3,0.1

Type RM Length L Ch R = 1 ,1166    ,165.9,167.3,166.9
XS GIS Cut Line= 4
2301672.07964546750389.3967650452301438.73392426750034.279557477
2301282.59790483749967.594958728  2301146.189121 749839.78853064
#Sta/Elev= 30
       0 1997.56    33.8 1995.87    57.7 1993.87    94.5 1989.07   141.6 1980.86
   158.9 1979.12   196.5    1978     230 1978.29   314.9 1977.19   393.2  1974.9
   411.9 1975.54   424.7 1976.97   433.8 1976.04   445.1 1975.87  450.81 1974.36
   458.2 1972.79   464.3 1974.36   468.5 1975.24   475.5 1975.42   485.6 1973.96
   492.9 1973.74   501.6 1975.44   523.4 1975.34   545.1 1978.71   562.5 1980.26
     645 1981.79   660.4 1983.52   691.5 1988.41   713.1 1990.29   781.6 1993.02
#Mann= 6, -1 ,  0
       0    0.05       0     340     0.1       0  450.81   0.045       0
   464.3     0.1       0  484.92    0.05       0   674.7     0.1       0
Bank Sta=450.81,464.3
XS Rating Curve= 0 ,0
Exp/Cntr(USF)=0,0
Exp/Cntr=0.3,0.1

Type RM Length L Ch R = 1 ,999     ,565.2,577.6,571.2
XS GIS Cut Line= 4
2301672.99660528750383.3779553182301522.45884433 749934.23833047
 2301409.7508435749847.574160693 2301183.7685198749791.215386146
#Sta/Elev= 30
       0 1997.54    23.4 1996.58    61.4 1993.86    81.4 1991.77   166.7 1980.84
   196.4 1978.68   286.8 1976.76   407.3 1975.21   435.3 1974.98   449.5 1975.48
   466.4 1974.63   530.3 1974.44   534.5 1974.34   541.7 1973.32   547.4 1972.22
   553.1 1973.31   562.4 1974.38   572.4 1973.74   581.6 1973.96   592.6 1974.76
   601.6 1976.37   612.8 1977.09   621.6 1976.78   691.7 1979.35   716.4 1979.75
   734.6 1982.49     774 1991.76   786.5 1993.72   815.4 1996.34   848.8    1997
#Mann= 6, -1 ,  0
       0    0.05       0   513.7     0.1       0   541.7   0.045       0
   553.1     0.1       0   603.7    0.05       0  755.87     0.1       0
#XS Ineff= 2 , 0
          448.65  1977.9
Permanent Ineff=
       F       F
Bank Sta=541.7,553.1
XS Rating Curve= 0 ,0
Exp/Cntr(USF)=0,0
Exp/Cntr=0.3,0.1

Type RM Length L Ch R = 1 ,421     ,264.6,258.4,243.4
XS GIS Cut Line= 3
 2301771.4872176750471.1153451822301620.90665114750205.376092686
2301728.60709841749352.887606546
#Sta/Elev= 30
       0 2003.42    71.6 2002.64   163.1  1996.6   193.3 1993.71   297.3  1980.6
   329.8 1978.77   515.3 1975.54   587.9 1974.62   616.4 1975.04   761.2  1971.7
     862 1973.03   870.1 1971.56   886.2  1971.9  890.171970.699   894.3 1969.08
   898.3 1968.99  903.371970.788   909.9 1975.11   914.4 1975.98   949.3 1976.94
     971 1979.16    1003 1979.64  1007.2 1981.09  1015.2 1987.14  1019.3  1988.6
  1043.5 1990.95  1059.6 1994.53  1079.7 2002.02  1128.3 2024.02  1164.7 2041.64
#Mann= 7, -1 ,  0
       0    0.05       0  605.44     0.1       0  805.44    0.05       0
  890.17   0.045       0  903.37    0.05       0  905.44    0.06       0
 1095.44     0.1       0
Bank Sta=890.17,903.37
XS Rating Curve= 0 ,0
Exp/Cntr=0.3,0.1

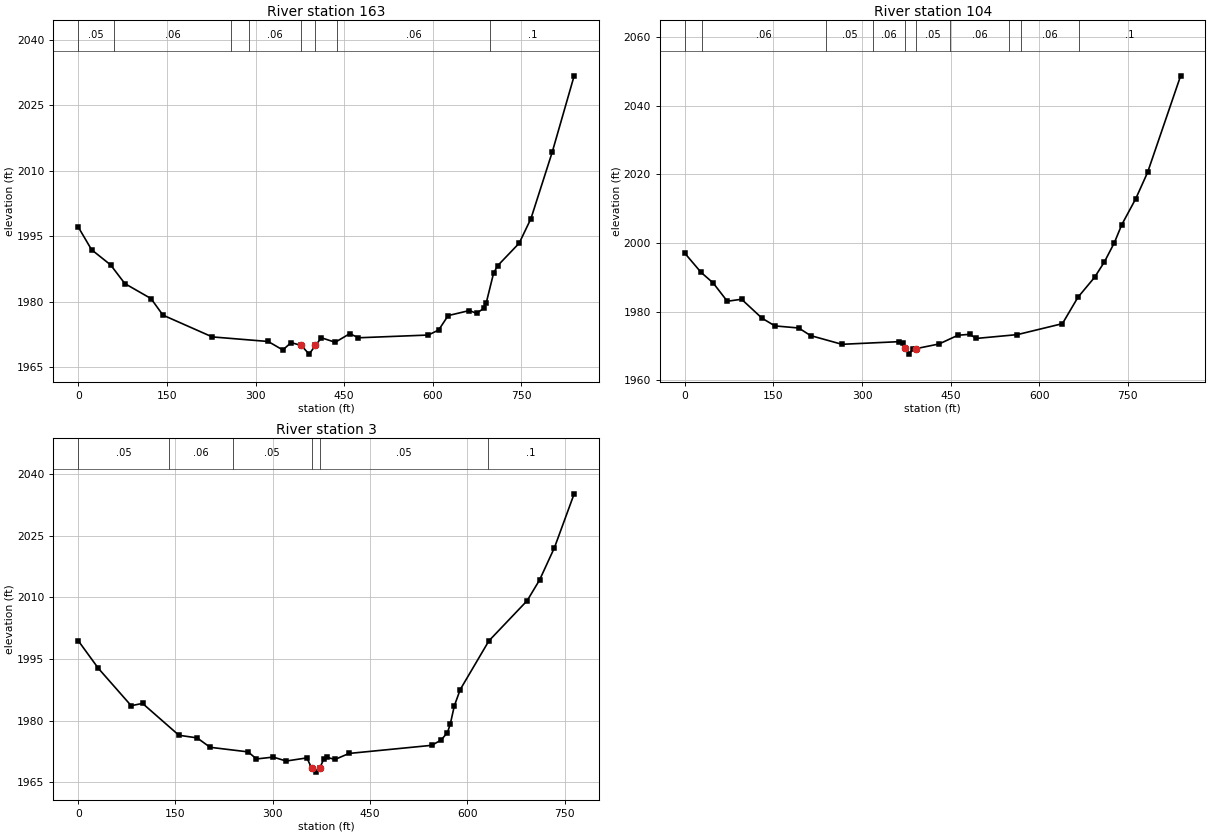
Type RM Length L Ch R = 1 ,163     ,57.7,58.9,60.9
XS GIS Cut Line= 4
 2302066.7114364750071.6368866932302042.45127361749854.409395897
2301741.94449045749607.6927928472301735.47914748749376.055160215
#Sta/Elev= 30
       0 1997.13    22.6 1991.91    54.8 1988.43    78.9 1984.14   123.2  1980.7
   143.3 1976.91   226.8 1971.91   321.4 1970.86   346.1 1968.92   360.3  1970.6
   377.4 1969.95   390.7 1967.96   401.31969.945   411.5 1971.71   434.8 1970.68
   459.6 1972.66     474 1971.71   592.4 1972.34   609.9  1973.5   625.9  1976.8
   661.9 1977.96   673.9 1977.32   685.9 1978.43   690.5 1979.79   702.8 1986.55
   709.9 1988.28     746 1993.39     766 1999.05     802  2014.3   839.1  2031.8
#Mann= 8, -1 ,  0
       0    0.05       0      60    0.06       0  258.58    0.05       0
  288.58    0.06       0   377.4   0.045       0   401.3    0.07       0
  438.58    0.06       0  697.39     0.1       0
Bank Sta=377.4,401.3
XS Rating Curve= 0 ,0
Exp/Cntr=0.3,0.1

Type RM Length L Ch R = 1 ,104     ,97.9,101.5,107.8
XS GIS Cut Line= 4
2302112.88307096750040.8381238042302088.62290817749823.610633008
2301788.11612501749576.8940299582301781.65078204749345.256397326
#Sta/Elev= 30
       0 1997.08    27.8 1991.44      48 1988.41    72.1 1983.05    96.3 1983.63
   130.7 1978.13   152.6 1975.87   192.9 1975.26     213 1973.05   266.1 1970.51
   362.7 1971.28   369.2 1970.75  372.841969.502   379.6 1967.65   385.5 1969.02
  391.931969.262   430.4 1970.61   462.4 1973.15   482.1 1973.41   493.5 1972.22
   562.8 1973.33   639.1 1976.52   665.4 1984.21   693.6 1990.03   710.1 1994.49
   727.1 2000.13   739.4  2005.3   763.2 2012.91   783.2 2020.56   839.1 2048.69
#Mann= 10, -1 ,  0
       0    0.05       0      30    0.06       0  238.58    0.05       0
  318.58    0.06       0  372.84   0.045       0  391.93    0.05       0
  448.58    0.06       0  548.58    0.05       0  568.58    0.06       0
  667.39     0.1       0
Bank Sta=372.84,391.93
XS Rating Curve= 0 ,0
Exp/Cntr=0.3,0.1

Type RM Length L Ch R = 1 ,3       ,477.7,477.7,477.7
XS GIS Cut Line= 4
2302123.75067491750048.1764078922302109.59339622749820.372923585
2302036.23295212749641.4764020092301836.74402519749362.191904298
#Sta/Elev= 30
       0 1999.46    31.1 1992.71    81.7 1983.62    99.2 1984.18   155.3 1976.42
   183.4 1975.78   203.4 1973.49     262 1972.37   274.9 1970.65   300.9  1971.1
   320.7 1970.14   352.7 1970.91   360.11968.354   366.7 1967.44   372.8 1968.55
   378.9 1970.68     383 1971.07     396 1970.53   417.6 1971.99   545.2 1973.97
   559.5 1975.24   569.4 1977.07   573.8 1979.16     580 1983.57   589.1 1987.55
   633.3 1999.41   692.3  2009.2   711.5 2014.25   734.4 2022.12   764.8 2035.23
#Mann= 6, -1 ,  0
       0    0.05       0     140    0.06       0  238.24    0.05       0
   360.1   0.045       0   372.8    0.05       0   631.6     0.1       0
Bank Sta=360.1,372.8
XS Rating Curve= 0 ,0
Exp/Cntr=0.3,0.1
LCMann Table=0

Chan Stop Cuts=-1
Use User Specified Reach Order=0
Composite Channel Slope=5